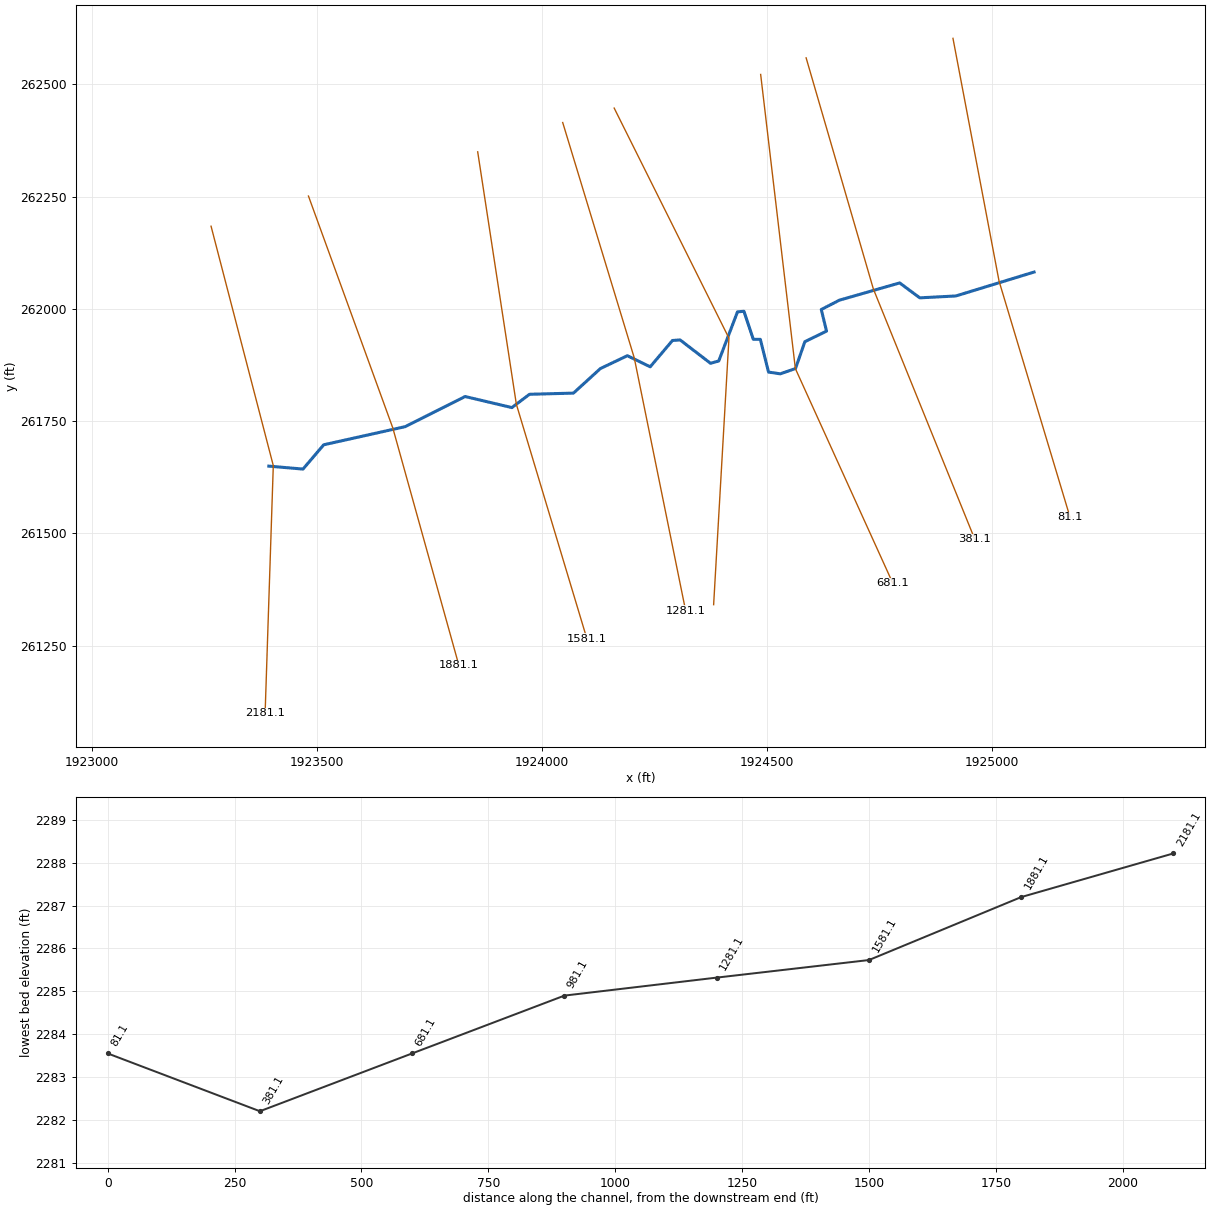
--- GldFrk.prj (project) ---

Proj Title=GldFrk
Current Plan=p01
Default Exp/Contr=0,0
English Units
Geom File=g01
Flow File=f01
Plan File=p01
BEGIN DESCRIPTION:
END DESCRIPTION:
DSS Export Rating Curves= 0
DSS Export Rating Curve Sorted= 0
DSS Export Volume Flow Curves= 0
DXF OffsetX= 0
DXF OffsetY= 0
DXF ScaleX= 0
DXF ScaleY= 0

--- GldFrk.p01 (plan) ---

Plan Title=Floodplain
Program Version=4.00
Geom File=g01
Flow File=f01
K Sum by GR=0
Std Step Tol=0.01
Critical Tol=0.01
Num of Std Step Trials=20
Max Error Tol=0.3
Flow Tol Ratio=0.001
Split Flow NTrial=30
Split Flow Tol=0.02
Split Flow Ratio=0.02
Log Output Level=0
Friction Slope Method=1
Unsteady Friction Slope Method=2
Unsteady Bridges Friction Slope Method=1
Global Log Level=0
CheckData=False
Run HTab=0
Run UNet=0
Run PostProcess=0
UNET Theta=0
UNET Theta Warmup=0
UNET ZTol=0
UNET ZSATol=0
UNET MxIter=0
UNET MaxInSteps=0
UNET DtIC=0
UNET DtMin=0
UNET MaxCRTS=0
UNET WFStab=0
UNET SFStab=0
UNET WFX=0
UNET SFX=0
UNET DSS MLevel=0
UNET DZMax Abort=0
UNET Convert EG Bridges=0
UNET Use Existing IB Tables=0
UNET Froude Limit=0
UNET Froude Power=0
Write IC File=0
Echo Input=False
Echo Output=False
Write Detailed=0

--- GldFrk.f01 (steady flow) ---

Flow Title=NFF Regression Equation
Program Version=4.00
Number of Profiles=1
Profile Names=P100yr
River Rch & RM=GldFrk,Main      ,2181.1
690.3383
River Rch & RM=GldFrk,Main      ,81.1
699.9431
Boundary for River Rch & Prof#=GldFrk,Main      ,1
Up Type=0
Dn Type=3
Dn Slope=0.001158

--- GldFrk.g01 (geometry) ---

Geom Title=USGS 3m DEM
Program Version=4.10

River Reach=GldFrk          ,Main
Reach XY= 30
     1923392.623      261649.717     1923468.627      261643.156
     1923514.689      261697.286     1923695.894      261737.708
     1923829.051      261804.809     1923933.024      261780.167
     1923972.213      261809.783     1924069.904      261812.387
     1924129.822      261867.093      1924189.74      261895.748
     1924240.539      261870.999     1924290.036      261929.612
      1924306.97      261930.914     1924374.701      261878.812
     1924392.937      261884.021      1924434.62      261993.435
     1924448.949      261994.737     1924469.788      261932.214
     1924485.419      261932.214     1924503.653      261859.271
     1924529.704      261855.363      1924563.57      261867.085
     1924584.412      261927.002     1924632.607      261950.447
     1924620.885      261998.642     1924661.264      262019.482
     1924795.155      262057.938      1924839.89       262024.68
     1924919.902      262028.798     1925094.057      262082.115

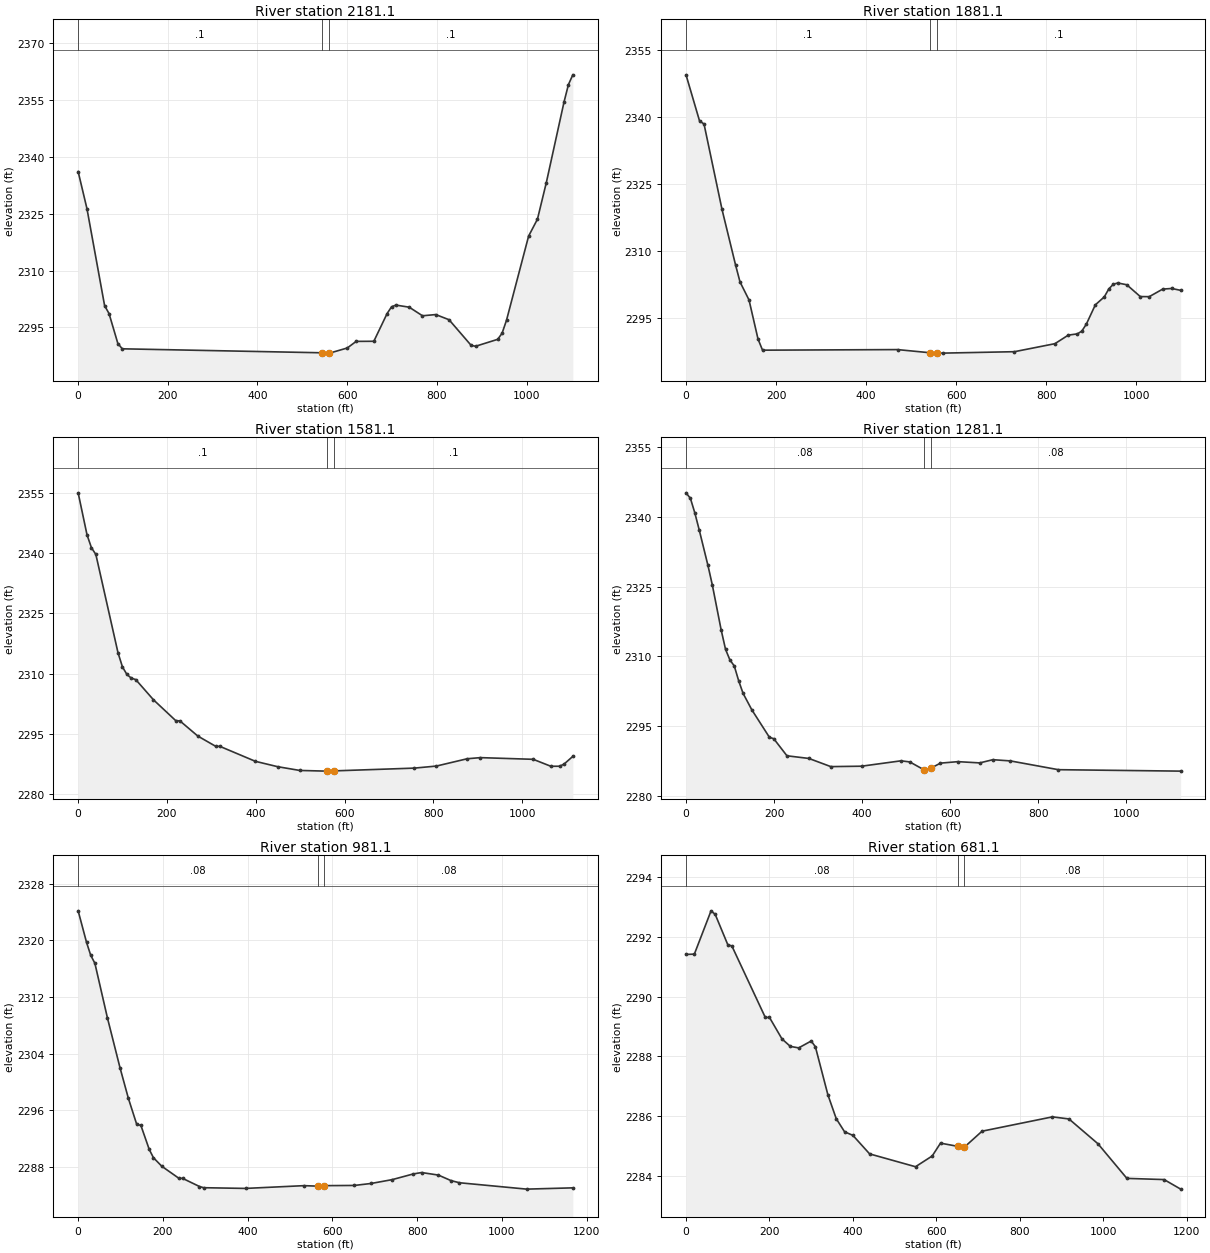
Type RM Length L Ch R = 1 ,2181.1  ,297.2,300,307.4
XS GIS Cut Line= 3
     1923264.196      262184.243     1923402.556      261650.876
     1923384.361      261098.856
#Sta/Elev= 30
       0 2336.14    19.7 2326.33      59 2300.76    68.9 2298.66    88.6 2290.75
    98.4 2289.36   543.5 2288.31   558.5 2288.24   560.9 2288.22   600.3 2289.58
   620.1 2291.32   659.5 2291.35   689.1 2298.67     699 2300.45   708.8  2300.9
   738.4 2300.35     768 2298.08   797.6  2298.4   827.2 2297.04   876.5 2290.27
   886.4 2290.03   935.7 2291.86   945.5 2293.46   955.4  2296.9  1004.7 2319.12
  1024.4 2323.58  1044.2 2333.23  1083.6 2354.47  1093.5 2359.11  1103.3 2361.69
#Mann= 3 , 0 , 0
       0      .1       0   543.5    .045       0   558.5      .1       0
Bank Sta=543.5,558.5
XS Rating Curve= 0 ,0
Exp/Cntr=0.3,0.1

Type RM Length L Ch R = 1 ,1881.1  ,303.7,300,301.4
XS GIS Cut Line= 3
     1923480.759      262251.414     1923668.268      261734.805
     1923815.133      261206.067
#Sta/Elev= 30
       0  2349.4      30 2339.11      40  2338.4    79.9 2319.33   109.9 2306.95
   119.9 2303.11   139.9 2299.08   159.9 2290.34   169.9 2287.86   469.6 2287.99
   542.1 2287.28   557.1 2287.22   569.5  2287.2   729.2 2287.52     819 2289.31
   848.9 2291.23   868.9  2291.5   878.8 2292.12   888.8 2293.67   908.8 2297.99
   928.7 2299.77   938.7 2301.55   948.7 2302.59   958.7 2302.88   978.6 2302.48
  1008.6 2299.84  1028.5 2299.82  1058.4 2301.51  1078.4 2301.65  1098.3 2301.23
#Mann= 3 , 0 , 0
       0      .1       0   542.1    .045       0   557.1      .1       0
Bank Sta=542.1,557.1
XS Rating Curve= 0 ,0
Exp/Cntr=0.3,0.1

Type RM Length L Ch R = 1 ,1581.1  ,294.1,300,306.4
XS GIS Cut Line= 3
     1923857.018      262350.016     1923942.946      261787.665
     1924099.706      261265.444
#Sta/Elev= 30
       0 2355.01      20 2344.54    29.9 2341.36    39.9 2339.66    89.8 2315.18
    99.8 2311.67   109.8  2309.8   119.8 2308.87   129.7 2308.52   169.7 2303.48
   219.6 2298.32   229.6  2298.2   269.5 2294.46   309.4 2291.93   319.4 2291.89
   399.2 2288.17   449.1 2286.84     499  2285.9   558.9 2285.73   561.4 2285.74
   576.4 2285.79   757.2 2286.48   806.8 2286.99   876.2 2288.81   905.9 2289.09
  1024.9 2288.67  1064.6 2286.94  1084.4 2286.95  1094.3 2287.48  1114.1  2289.4
#Mann= 3 , 0 , 0
       0      .1       0   561.4    .045       0   576.4      .1       0
Bank Sta=561.4,576.4
XS Rating Curve= 0 ,0
Exp/Cntr=0.3,0.1

Type RM Length L Ch R = 1 ,1281.1  ,297.1,300,252
XS GIS Cut Line= 3
     1924046.022      262415.298     1924205.086      261890.934
     1924319.419      261327.173
#Sta/Elev= 30
       0 2345.21      10 2344.02    19.9 2340.93    29.9 2337.26    49.8 2329.59
    59.8 2325.36    79.7 2315.76    89.7 2311.55    99.6 2309.26   109.6 2307.95
   119.6 2304.76   129.5 2302.07   149.4 2298.52   189.3 2292.61   199.3 2292.29
   229.2 2288.62     279 2288.05   328.8 2286.29   398.5 2286.38   488.2 2287.54
   508.1  2287.3   540.5  2285.6   555.5 2285.93   577.7 2287.04   617.4 2287.36
     667 2287.09   696.7 2287.78   736.4 2287.52   845.5 2285.63  1123.2 2285.32
#Mann= 3 , 0 , 0
       0     .08       0   540.5    .045       0   555.5     .08       0
Bank Sta=540.5,555.5
XS Rating Curve= 0 ,0
Exp/Cntr=0.3,0.1

Type RM Length L Ch R = 1 ,981.1   ,332.9,300,316.2
XS GIS Cut Line= 3
     1924160.445      262447.476      1924415.65      261934.809
     1924381.585       261341.04
#Sta/Elev= 30
       0 2324.15    19.8  2319.7    29.6 2317.89    39.5 2316.75    69.1 2309.05
    98.7 2302.04   118.5 2297.71   138.2 2294.04   148.1 2293.88   167.8 2290.49
   177.7 2289.33   197.5 2288.12     237 2286.46   246.8 2286.41   286.3 2285.27
   296.2  2285.1     395    2285   533.2 2285.39   565.2 2285.32   580.2 2285.39
     652 2285.42   691.6  2285.7   741.2 2286.24   790.8 2287.04   810.6 2287.24
   850.2 2286.88     880  2286.1   899.8  2285.8  1058.4  2284.9  1167.4 2285.08
#Mann= 3 , 0 , 0
       0     .08       0   565.2    .045       0   580.2     .08       0
Bank Sta=565.2,580.2
XS Rating Curve= 0 ,0
Exp/Cntr=0.3,0.1

Type RM Length L Ch R = 1 ,681.1   ,266.1,300,292.6
XS GIS Cut Line= 3
     1924486.142      262522.405     1924563.296       261866.99
     1924780.202      261388.267
#Sta/Elev= 30
       0 2291.41      20 2291.42      60 2292.87      70 2292.75     100 2291.74
     110 2291.69     190  2289.3     200  2289.3     230 2288.58     250 2288.33
     270 2288.28     300 2288.51     310 2288.32     340 2286.71     360 2285.91
     380 2285.47     400 2285.35     440 2284.73     550  2284.3     590 2284.66
   609.9 2285.09   652.4 2284.98   667.4 2284.96   709.5 2285.49   878.1 2285.97
   917.8  2285.9   987.2 2285.07  1056.6 2283.91  1145.8 2283.87  1185.5 2283.55
#Mann= 3 , 0 , 0
       0     .08       0   652.4    .045       0   667.4     .08       0
Bank Sta=652.4,667.4
XS Rating Curve= 0 ,0
Exp/Cntr=0.3,0.1

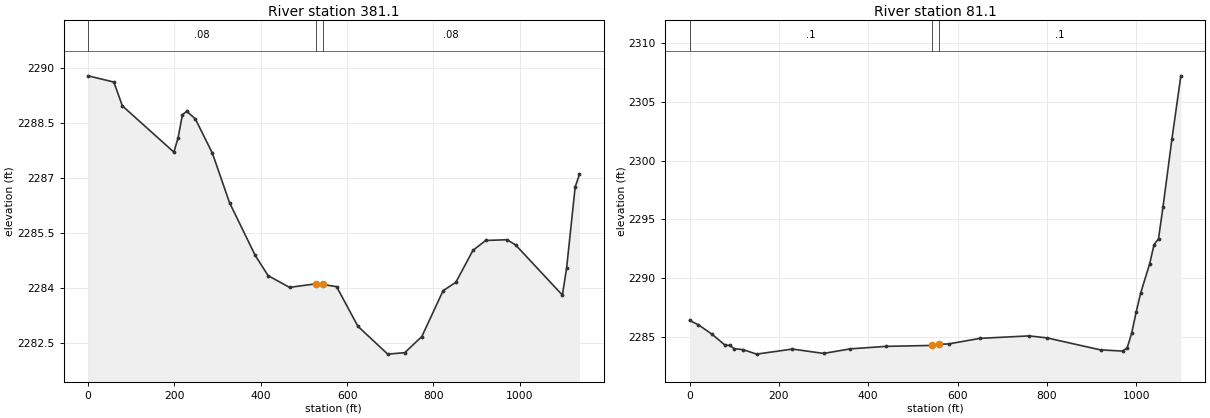
Type RM Length L Ch R = 1 ,381.1   ,303.4,300,295.7
XS GIS Cut Line= 3
     1924587.199       262559.39     1924736.669      262044.523
     1924962.344      261486.461
#Sta/Elev= 30
       0 2289.79    59.6 2289.62    79.4 2288.97   198.6 2287.71   208.5  2288.1
   218.4 2288.73   228.4 2288.82   248.2 2288.62   287.9 2287.68   327.6 2286.33
   387.2 2284.89     417 2284.34   466.6 2284.02   528.6 2284.12   543.6  2284.1
   575.6 2284.04   624.9 2282.96     694  2282.2   733.5 2282.24     773 2282.68
   822.3 2283.93   851.9 2284.16   891.4 2285.03     921  2285.3   970.3 2285.32
   990.1 2285.18  1098.6 2283.81  1108.5 2284.56  1128.2 2286.76  1138.1  2287.1
#Mann= 3 , 0 , 0
       0     .08       0   528.6    .045       0   543.6     .08       0
Bank Sta=528.6,543.6
XS Rating Curve= 0 ,0
Exp/Cntr=0.3,0.1

Type RM Length L Ch R = 1 ,81.1    ,83.7,81.1,76.1
XS GIS Cut Line= 3
     1924913.703      262602.844       1925016.1      262062.162
     1925173.947      261536.049
#Sta/Elev= 30
       0 2286.42      20 2286.04      50 2285.25      80  2284.3      90  2284.3
     100 2284.01   120.1 2283.93   150.1 2283.55   230.1 2283.98   300.2 2283.61
   360.2    2284   440.2 2284.21   542.8 2284.29   557.8 2284.38   580.2 2284.42
   650.2 2284.89     760  2285.1     800 2284.93   919.8 2283.91   969.7 2283.81
   979.7  2284.1   989.7 2285.36   999.7 2287.14  1009.7 2288.75  1029.7 2291.21
  1039.6 2292.85  1049.6 2293.35  1059.6 2296.04  1079.6 2301.82  1099.6  2307.2
#Mann= 3 , 0 , 0
       0      .1       0   542.8    .045       0   557.8      .1       0
Bank Sta=542.8,557.8
XS Rating Curve= 0 ,0
Exp/Cntr=0.3,0.1

Chan Stop Cuts=-1
Use User Specified Reach Order=0
Composite Channel Slope=5